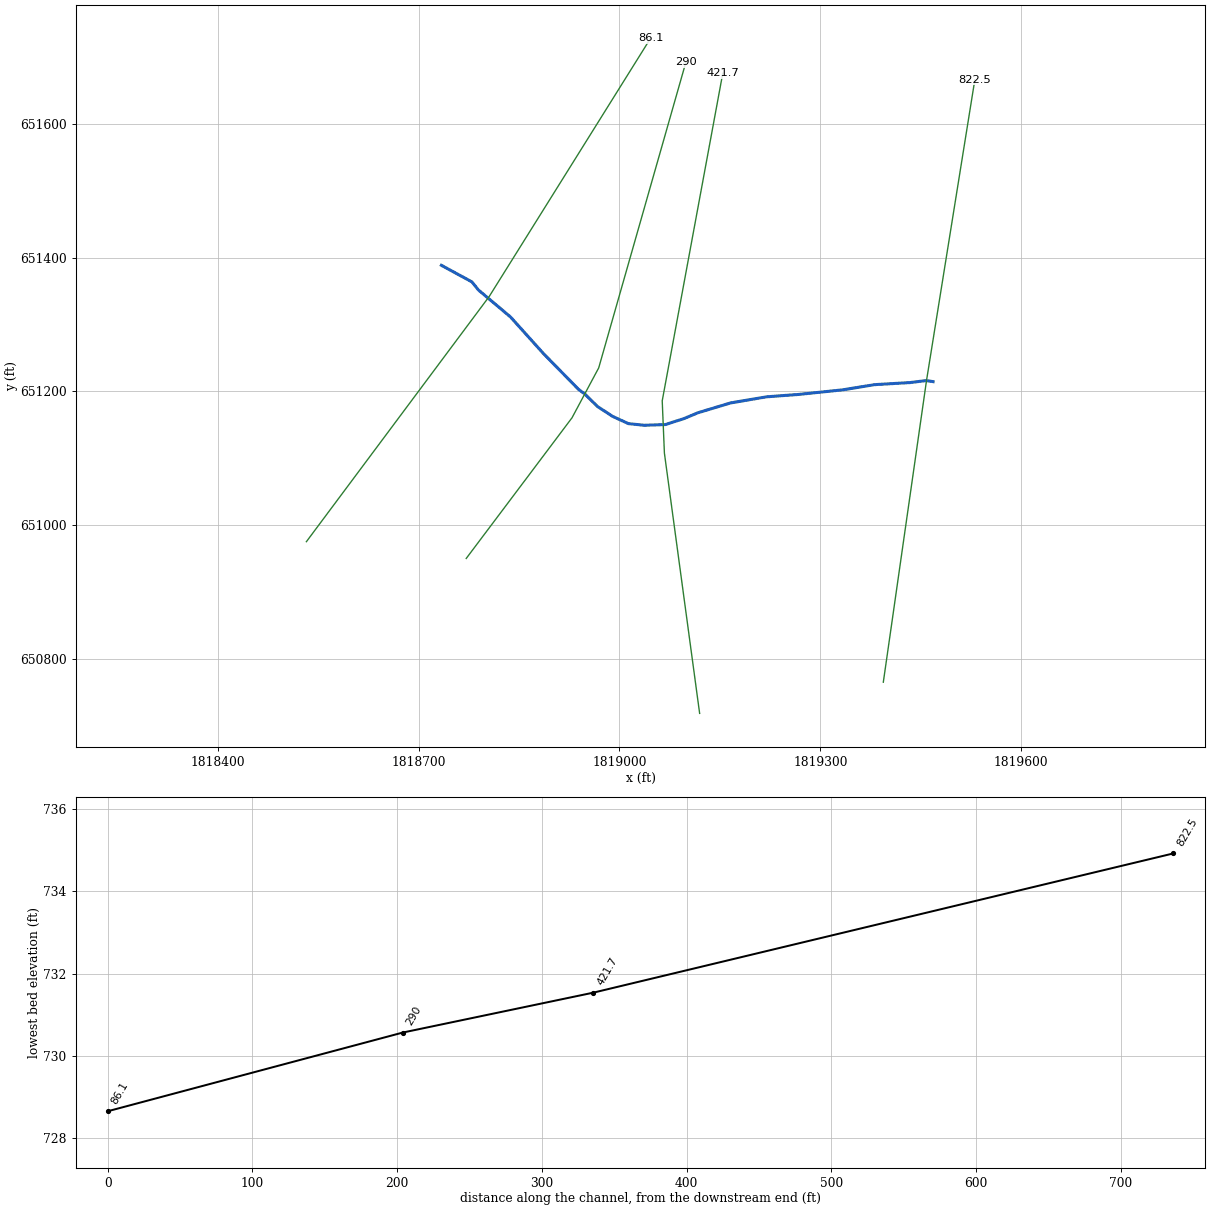
--- RFFrzcpCrk.prj (project) ---

Proj Title=RFFrzcpCrk
Current Plan=p01
Default Exp/Contr=0,0
English Units
Geom File=g01
Flow File=f01
Plan File=p01
BEGIN DESCRIPTION:
AMEC Environment & Infrastructure, 2013
Projection: NAD 1983 State Plane West Virginia South FIPS 4702 (US Feet)
Vertical Datum: NAVD 1988
END DESCRIPTION:
DSS Export Rating Curves= 0
DSS Export Rating Curve Sorted= 0
DSS Export Volume Flow Curves= 0
DXF OffsetX= 0
DXF OffsetY= 0
DXF ScaleX= 0
DXF ScaleY= 0

--- RFFrzcpCrk.p01 (plan) ---

Plan Title=Floodplain
Program Version=4.00
Geom File=g01
Flow File=f01
K Sum by GR=0
Std Step Tol=0.01
Critical Tol=0.01
Num of Std Step Trials=20
Max Error Tol=0.3
Flow Tol Ratio=0.001
Split Flow NTrial=30
Split Flow Tol=0.02
Split Flow Ratio=0.02
Log Output Level=0
Friction Slope Method=1
Unsteady Friction Slope Method=2
Unsteady Bridges Friction Slope Method=1
Global Log Level=0
CheckData=False
Run HTab=0
Run UNet=0
Run PostProcess=0
UNET Theta=0
UNET Theta Warmup=0
UNET ZTol=0
UNET ZSATol=0
UNET MxIter=0
UNET MaxInSteps=0
UNET DtIC=0
UNET DtMin=0
UNET MaxCRTS=0
UNET WFStab=0
UNET SFStab=0
UNET WFX=0
UNET SFX=0
UNET DSS MLevel=0
UNET DZMax Abort=0
UNET Convert EG Bridges=0
UNET Use Existing IB Tables=0
UNET Froude Limit=0
UNET Froude Power=0
Write IC File=0
Echo Input=False
Echo Output=False
Write Detailed=0

--- RFFrzcpCrk.f01 (steady flow) ---

Flow Title=NFF Regression Equation
Program Version=4.10
Number of Profiles= 1
Profile Names=P100yr
River Rch & RM=RFFrzcpCrk,Main            ,822.5
833.9563
River Rch & RM=RFFrzcpCrk,Main            ,290
891.6806
River Rch & RM=RFFrzcpCrk,Main            ,86.1
894.6682
Boundary for River Rch & Prof#=RFFrzcpCrk,Main            , 1
Up Type= 0
Dn Type= 3
Dn Slope=0.00951
DSS Import GetInterval= 0
DSS Import GetPeak= 0
DSS Import FillOption= 0

--- RFFrzcpCrk.g01 (geometry) ---

Geom Title=USGS 3m DEM
Program Version=4.10

River Reach=RFFrzcpCrk      ,Main
Reach XY= 23
     1819468.438      651214.592     1819458.272      651216.225
      1819434.69      651213.277     1819380.945      651210.116
      1819333.61      651202.378      1819266.77      651195.434
     1819219.895      651191.962      1819168.68      651183.281
     1819166.404       651182.98      1819117.03       651168.09
     1819096.532      651159.494     1819068.549      651150.512
     1819037.082      651149.427     1819013.345      651151.882
     1818989.339      651162.925     1818967.117      651177.508
     1818947.782      651196.498     1818939.079      651202.812
     1818885.911      651257.066     1818837.082      651311.319
     1818789.339      651351.467     1818779.607      651363.573
     1818734.001      651388.359

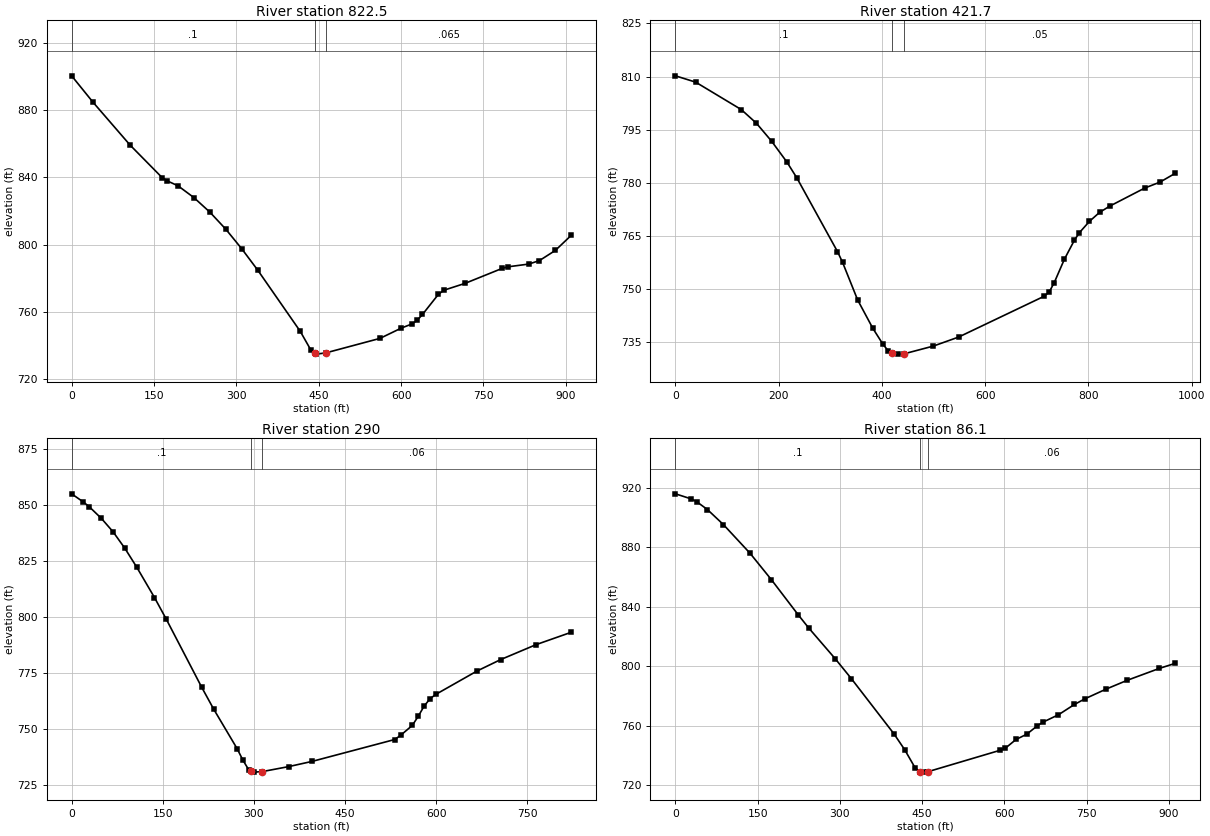
Type RM Length L Ch R = 1 ,822.5   ,396.4,400.7,405.1
XS GIS Cut Line= 3
     1819394.061      650765.692     1819458.565      651216.178
     1819530.732      651665.404
#Sta/Elev= 30
       0  900.24    38.7  884.64   106.5  859.08   164.6  839.84   174.3  837.79
   193.6  834.94   222.7   827.9   251.8  819.25   280.8  809.12   309.8  797.51
   338.9  784.83   416.4  748.45   435.7  737.35  442.61  735.51   445.4  734.92
   462.6  735.63   561.6  744.27   600.3  750.37   619.6  752.82   629.3  754.97
     639  758.48     668  770.43   677.7  772.85   716.5  776.95   784.2  785.86
   793.9  786.75   832.6  788.42     852  790.48     881  796.52   910.1  805.54
#Mann= 3 , 0 , 0
       0      .1       0  442.61    .045       0   462.6    .065       0
Bank Sta=442.61,462.6
XS Rating Curve= 0 ,0
Exp/Cntr=0.3,0.1

Type RM Length L Ch R = 1 ,421.7   ,143.5,131.8,119.4
XS GIS Cut Line= 4
     1819119.695      650719.115     1819067.074      651107.847
     1819063.819      651185.972     1819154.261      651675.187
#Sta/Elev= 30
       0   810.2    39.2  808.41   127.5  800.66   156.9  796.79   186.3  791.71
   215.8  785.85   235.4  781.29   313.8  760.54   323.6  757.52     353  746.83
   382.5   738.8     402  734.32   411.8  732.54  420.44  731.72   431.4  731.54
   442.4  731.61   499.7  733.82   548.5  736.36   714.3   747.9   724.1  749.12
   733.8  751.75   753.4  758.34   772.9  763.75   782.6  765.88   802.1  769.08
   821.6   771.6   841.2  773.36   909.4   778.5   938.7  780.16     968  782.63
#Mann= 3 , 0 , 0
       0      .1       0  420.44    .045       0   442.4     .05       0
Bank Sta=420.44,442.4
XS Rating Curve= 0 ,0
Exp/Cntr=0.3,0.1

Type RM Length L Ch R = 1 ,290     ,207.3,203.8,201.8
XS GIS Cut Line= 4
     1818771.067      650950.512     1818929.053      651160.581
     1818968.984      651235.234     1819099.192      651691.831
#Sta/Elev= 30
       0  855.04    19.5  851.33    29.2   849.2    48.7  844.12    68.2  838.04
    87.6  830.67   107.1  822.24   136.3  808.67   155.8  798.94   214.2  768.44
   233.6  758.81   272.2  741.12   281.7     736   291.1  731.74   295.7  731.17
   300.5  730.57  313.72  730.81   357.2  733.04     396  735.39   531.6  745.15
   541.3     747   560.7  751.49   570.4  755.56   580.1  760.11   589.8   763.4
   599.4  765.36   667.3  775.82     706   780.9   764.2  787.58   822.3  793.13
#Mann= 3 , 0 , 0
       0      .1       0   295.7    .045       0  313.72     .06       0
Bank Sta=295.7,313.72
XS Rating Curve= 0 ,0
Exp/Cntr=0.3,0.1

Type RM Length L Ch R = 1 ,86.1    ,82.8,86.1,87.8
XS GIS Cut Line= 3
      1818532.32      650975.545     1818805.414       651341.81
     1819046.359      651727.388
#Sta/Elev= 30
       0  915.89    29.2  912.42    38.9  910.55    58.3  905.31    87.5  895.18
   136.1  875.88     175  858.12   223.6  834.64     243  825.67   291.6  804.87
   320.8  791.58   398.6  754.41     418  743.84   437.4  731.41   446.4  728.99
   456.9  728.66   461.4  729.05   592.3  743.36     602  744.83   621.3  750.64
   640.7  754.14     660   759.8   669.7  762.16   698.7  767.26   727.7  774.16
   747.1  778.02   785.8  784.55   824.5   790.5   882.5  798.41   911.5  801.83
#Mann= 3 , 0 , 0
       0      .1       0   446.4    .045       0   461.4     .06       0
Bank Sta=446.4,461.4
XS Rating Curve= 0 ,0
Exp/Cntr=0.3,0.1

Chan Stop Cuts=-1
Use User Specified Reach Order=0
Composite Channel Slope=5